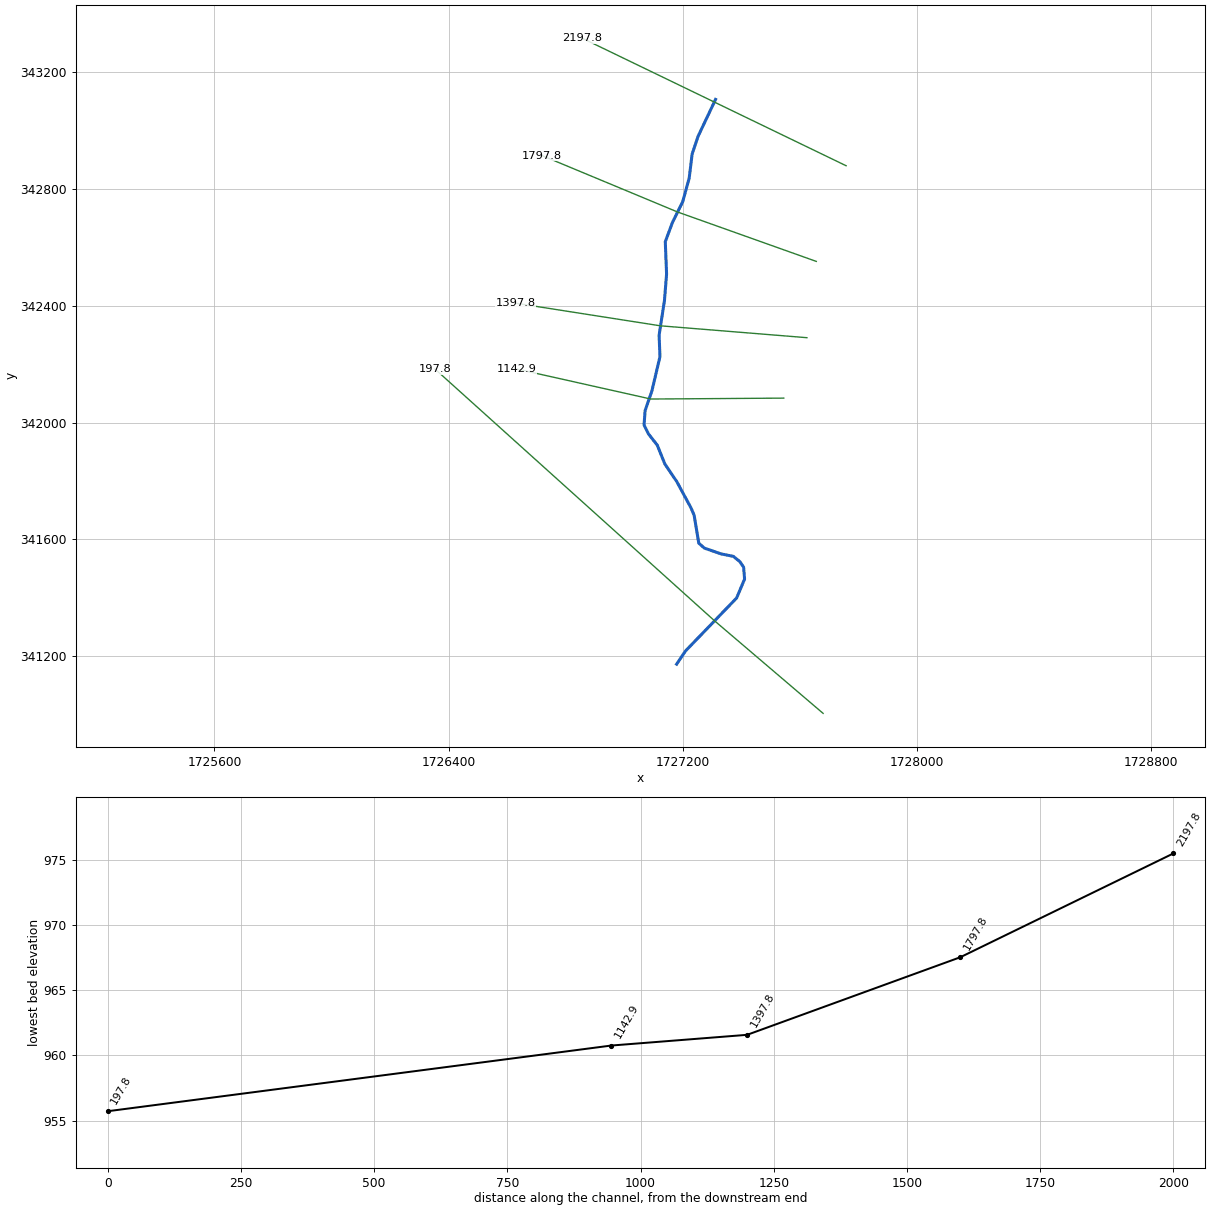
--- BgmnRnTr.prj (project) ---

Proj Title=BgmnRnTr
Current Plan=p01
Geom File=g01
Flow File=f01
Plan File=p01
DSS Export Rating Curves=0
DSS Export Rating Curve Sorted=0
DSS Export Volume Flow Curves=0
DXF OffsetX=0
DXF OffsetY=0
DXF ScaleX=0
DXF ScaleY=0

--- BgmnRnTr.p01 (plan) ---

Plan Title=Floodplain
Program Version=4.00
Geom File=g01
Flow File=f01
K Sum by GR=0
Std Step Tol=0.01
Critical Tol=0.01
Num of Std Step Trials=20
Max Error Tol=0.3
Flow Tol Ratio=0.001
Split Flow NTrial=30
Split Flow Tol=0.02
Split Flow Ratio=0.02
Log Output Level=0
Friction Slope Method=1
Unsteady Friction Slope Method=2
Unsteady Bridges Friction Slope Method=1
Global Log Level=0
CheckData=False
Run HTab=0
Run UNet=0
Run PostProcess=0
UNET Theta=0
UNET Theta Warmup=0
UNET ZTol=0
UNET ZSATol=0
UNET MxIter=0
UNET MaxInSteps=0
UNET DtIC=0
UNET DtMin=0
UNET MaxCRTS=0
UNET WFStab=0
UNET SFStab=0
UNET WFX=0
UNET SFX=0
UNET DSS MLevel=0
UNET DZMax Abort=0
UNET Convert EG Bridges=0
UNET Use Existing IB Tables=0
UNET Froude Limit=0
UNET Froude Power=0
Write IC File=0
Echo Input=False
Echo Output=False
Write Detailed=0

--- BgmnRnTr.f01 (steady flow) ---

Flow Title=NFF Regression Equation
Program Version=4.00
Number of Profiles=1
Profile Names=P100yr
River Rch & RM=BgmnRnTr,Main      ,2197.8
726.2800
River Rch & RM=BgmnRnTr,Main      ,197.8
755.7722
Boundary for River Rch & Prof#=BgmnRnTr,Main      ,1
Up Type=0
Dn Type=3
Dn Slope=0.002211

--- BgmnRnTr.g01 (geometry) ---

Geom Title=USGS 3m DEM
Program Version=4.00

River Reach=BgmnRnTr     ,Main
Reach XY= 30
     1727312.449      343107.063     1727252.766      342980.779
     1727232.444      342920.067     1727222.352      342837.687
     1727200.269      342756.801     1727165.531      342686.576
     1727140.637      342619.669     1727145.087      342509.214
     1727137.926      342418.943     1727119.518      342299.448
     1727122.515      342226.184     1727094.836      342108.382
     1727071.710      342041.341     1727068.109      341992.054
     1727083.422      341961.210     1727113.232      341923.119
     1727139.162      341858.591     1727180.104      341797.903
     1727228.823      341707.643     1727239.282      341682.802
     1727255.191      341587.297     1727274.000      341570.585
     1727330.982      341550.716     1727373.247      341542.176
     1727395.396      341524.222     1727408.372      341505.170
     1727411.578      341464.216     1727384.507      341399.660
     1727209.713      341218.118     1727179.396      341173.125

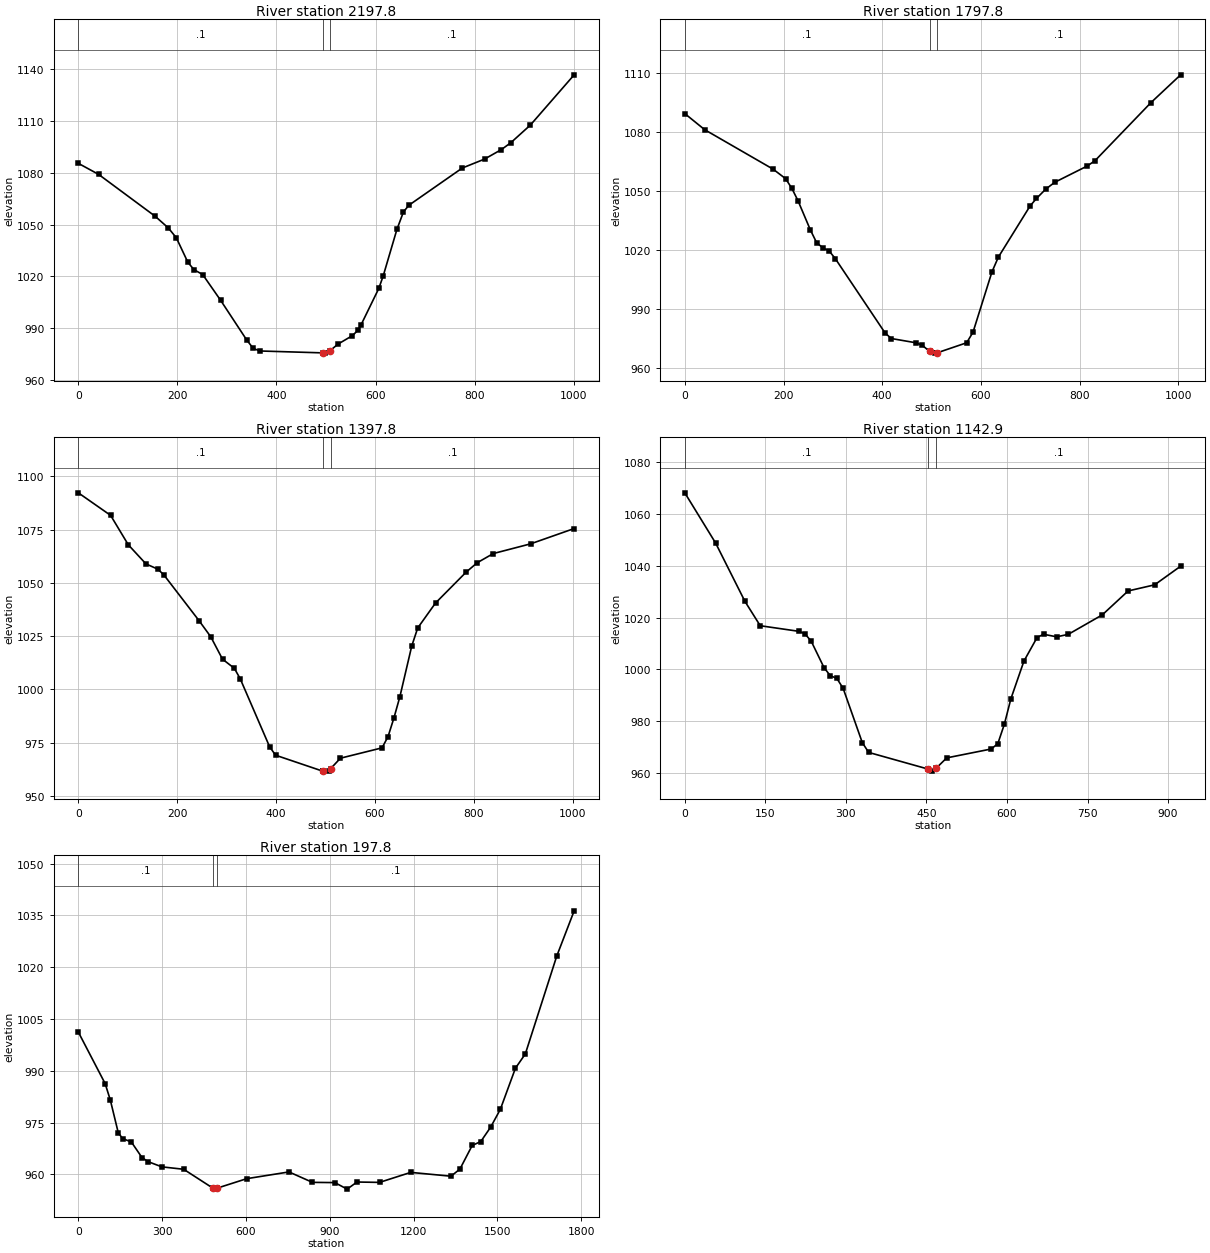
Type RM Length L Ch R = 1 ,2197.8,397.556,400,401.256
XS GIS Cut Line= 3
     1727758.553      342879.926     1727308.090      343098.063
     1726857.628      343316.200
#Sta/Elev= 30
       0 1085.47    40.8 1079.10   155.1 1054.80   181.5 1048.08   197.8 1042.35
   221.1 1028.14   233.4 1023.86   251.1 1021.00   287.1 1006.16   339.8  983.15
   353.0  978.25   366.2  976.72     493  975.62   498.1  975.47     508  976.86
   524.5  980.75   553.3  985.61   564.1  988.62   571.1  992.06   606.6 1012.97
   615.5 1020.22   643.2 1047.21   656.4 1057.33   667.3 1061.18   775.1 1082.75
   820.0 1087.93   854.3 1093.49   873.3 1097.47   912.5 1107.63  1001.0 1136.78
#Mann= 3 , 0 , 0
       0     0.1       0     493   0.045       0     508     0.1       0
Bank Sta=     493,     508
Exp/Cntr=0.3,0.1

Type RM Length L Ch R = 1 ,1797.8,394.047,400,405.468
XS GIS Cut Line= 3
     1727656.767      342552.280     1727182.778      342721.441
     1726720.208      342914.388
#Sta/Elev= 30
       0 1089.40    40.2 1081.22   178.9 1061.12   204.1 1056.31   216.7 1051.44
   229.3 1045.09   254.5 1030.14   267.1 1023.71   279.7 1021.07   292.3 1019.55
   304.9 1015.60   405.8  977.77   418.4  974.95   468.8  972.76   481.4  971.46
   495.8  968.43   506.7  967.52   510.8  967.64   571.0  972.79   583.9  978.17
   622.3 1008.88   635.3 1016.39   699.6 1042.43   712.5 1046.23   731.2 1050.95
   749.4 1054.43   815.4 1062.74   831.1 1065.45   944.1 1094.91  1004.5 1109.12
#Mann= 3 , 0 , 0
       0     0.1       0   495.8   0.045       0   510.8     0.1       0
Bank Sta=   495.8,   510.8
Exp/Cntr=0.3,0.1

Type RM Length L Ch R = 1 ,1397.8,253.905,254.841,253.386
XS GIS Cut Line= 3
     1727624.661      342291.029     1727123.466      342331.772
     1726629.521      342409.194
#Sta/Elev= 30
       0 1092.27    65.3 1081.68   101.1 1067.85   136.8 1058.89   160.6 1056.44
   172.5 1053.88   244.0 1032.28   267.8 1024.69   291.6 1014.15   315.5 1009.87
   327.4 1004.96   386.9  973.00   398.9  969.06   494.1  961.58   495.3  961.61
   506.1  961.71   510.3  962.75   530.1  967.65   614.2  972.51   626.3  977.73
   638.3  986.57   650.3  996.50   674.3 1020.32   686.4 1028.81   722.4 1040.52
   783.9 1054.93   806.5 1059.41   839.2 1063.75   914.7 1068.31  1002.8 1075.50
#Mann= 3 , 0 , 0
       0     0.1       0   495.3   0.045       0   510.3     0.1       0
Bank Sta=   495.3,   510.3
Exp/Cntr=0.3,0.1

Type RM Length L Ch R = 1 ,1142.9,960.025,945.159,933.749
XS GIS Cut Line= 3
     1727545.748      342084.081     1727091.325      342080.968
     1726633.790      342183.680
#Sta/Elev= 30
       0 1068.08    57.4 1048.71   112.0 1026.22   140.5 1016.83   211.8 1014.69
   223.7 1013.75   235.5 1010.83   259.3 1000.67   271.1  997.52   283.0  996.57
   294.9  992.68   330.5  971.79   342.4  967.98   452.6  961.58   461.3  960.76
   467.6  961.78   487.8  965.87   570.8  969.30   583.0  971.38   595.1  978.82
   607.3  988.66   631.6 1003.20   656.0 1012.26   668.1 1013.54   692.5 1012.55
   714.1 1013.50   777.6 1021.03   825.6 1030.24   875.0 1032.60   923.4 1039.79
#Mann= 3 , 0 , 0
       0     0.1       0   452.6   0.045       0   467.6     0.1       0
Bank Sta=   452.6,   467.6
Exp/Cntr=0.3,0.1

Type RM Length L Ch R = 1 ,197.8,195.183,197.757,200.941
XS GIS Cut Line= 3
     1727680.008      341004.474     1727308.918      341321.569
     1726353.667      342183.680
#Sta/Elev= 30
       0 1001.22    96.0  986.29   114.6  981.51   142.8  972.10   158.4  970.37
   189.7  969.40   227.7  964.89   249.3  963.70   299.0  962.18   377.1  961.48
   480.6  956.07   495.6  955.98   602.8  958.76   754.1  960.71   838.1  957.69
   918.2  957.62   962.2  955.73   997.6  957.79  1078.1  957.68  1190.0  960.58
  1334.0  959.47  1366.0  961.54  1409.8  968.37  1440.7  969.52  1476.1  973.70
  1510.7  978.85  1564.7  990.76  1600.1  994.89  1712.4 1023.19  1774.9 1036.34
#Mann= 3 , 0 , 0
       0     0.1       0   480.6   0.045       0   495.6     0.1       0
Bank Sta=   480.6,   495.6
Exp/Cntr=0.3,0.1